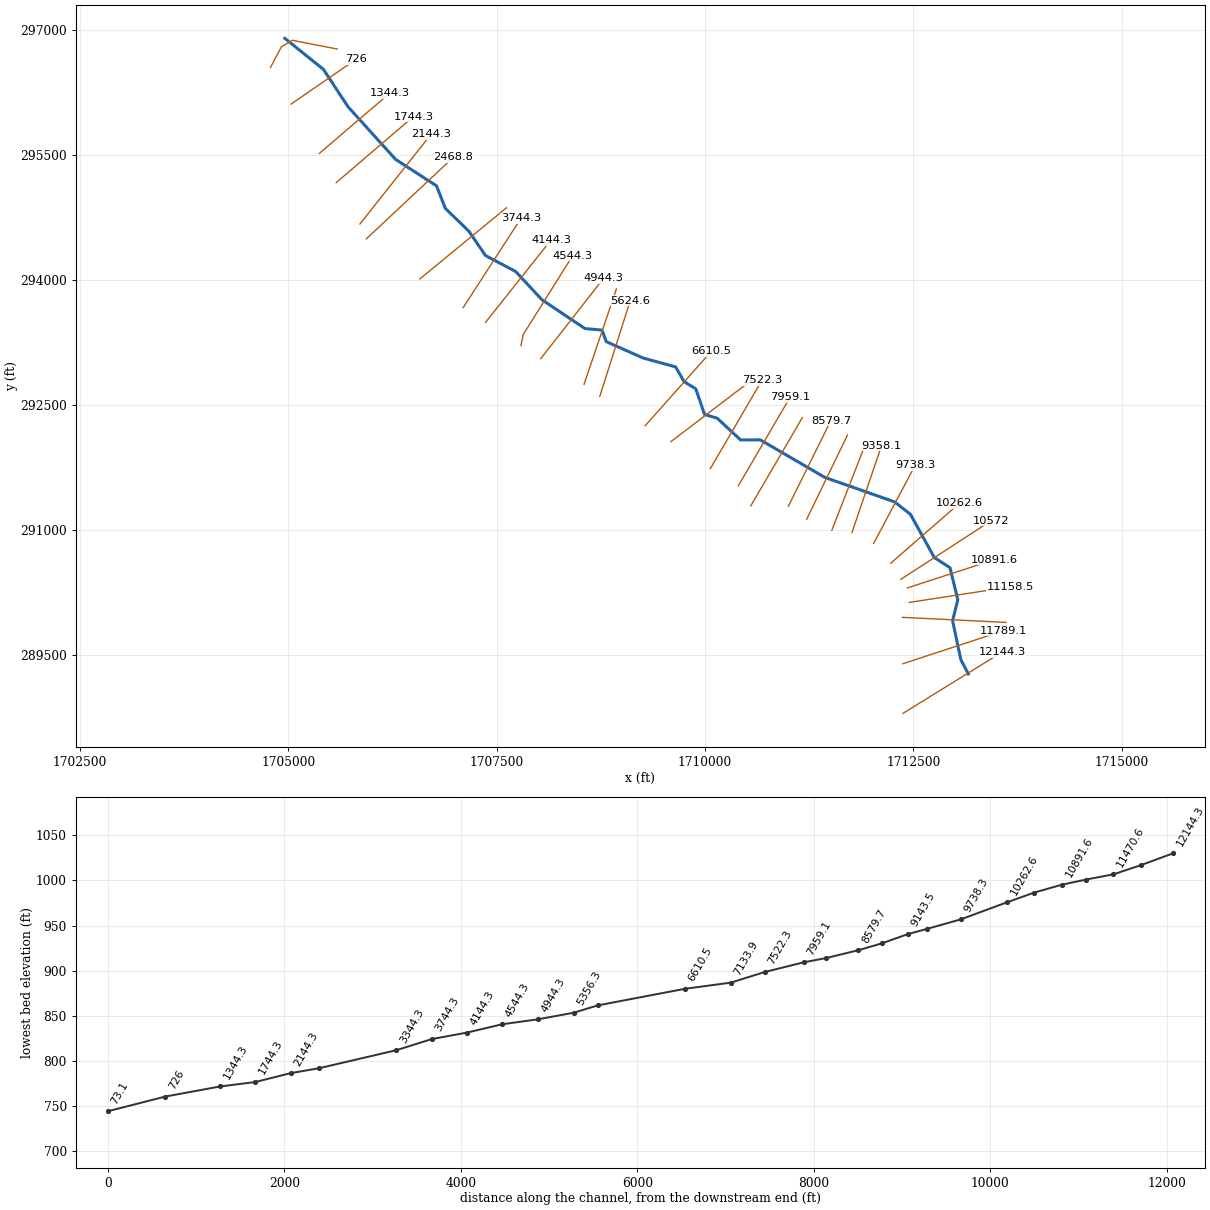
--- RIGHTRMCRK.prj (project) ---

Proj Title=RIGHTRMCRK
Current Plan=p01
Default Exp/Contr=0,0
English Units
Geom File=g01
Flow File=f01
Plan File=p01
BEGIN DESCRIPTION:
END DESCRIPTION:
DSS Export Rating Curves= 0
DSS Export Rating Curve Sorted= 0
DSS Export Volume Flow Curves= 0
DXF OffsetX= 0
DXF OffsetY= 0
DXF ScaleX= 0
DXF ScaleY= 0

--- RIGHTRMCRK.p01 (plan) ---

Plan Title=Floodplain
Program Version=4.00
Geom File=g01
Flow File=f01
K Sum by GR=0
Std Step Tol=0.01
Critical Tol=0.01
Num of Std Step Trials=20
Max Error Tol=0.3
Flow Tol Ratio=0.001
Split Flow NTrial=30
Split Flow Tol=0.02
Split Flow Ratio=0.02
Log Output Level=0
Friction Slope Method=1
Unsteady Friction Slope Method=2
Unsteady Bridges Friction Slope Method=1
Global Log Level=0
CheckData=False
Run HTab=0
Run UNet=0
Run PostProcess=0
UNET Theta=0
UNET Theta Warmup=0
UNET ZTol=0
UNET ZSATol=0
UNET MxIter=0
UNET MaxInSteps=0
UNET DtIC=0
UNET DtMin=0
UNET MaxCRTS=0
UNET WFStab=0
UNET SFStab=0
UNET WFX=0
UNET SFX=0
UNET DSS MLevel=0
UNET DZMax Abort=0
UNET Convert EG Bridges=0
UNET Use Existing IB Tables=0
UNET Froude Limit=0
UNET Froude Power=0
Write IC File=0
Echo Input=False
Echo Output=False
Write Detailed=0

--- RIGHTRMCRK.f01 (steady flow) ---

Flow Title=NFF Regression Equation
Program Version=4.00
Number of Profiles=1
Profile Names=P100yr
River Rch & RM=RIGHTRMCRK,Main      ,12144.3
947.6503
River Rch & RM=RIGHTRMCRK,Main      ,10572
1021.752
River Rch & RM=RIGHTRMCRK,Main      ,8213
1101.452
River Rch & RM=RIGHTRMCRK,Main      ,7959.1
1355.098
River Rch & RM=RIGHTRMCRK,Main      ,6610.5
1381.834
River Rch & RM=RIGHTRMCRK,Main      ,3744.3
1530.441
River Rch & RM=RIGHTRMCRK,Main      ,73.1
1630.195
Boundary for River Rch & Prof#=RIGHTRMCRK,Main      ,1
Up Type=0
Dn Type=3
Dn Slope=0.019161

--- RIGHTRMCRK.g01 (geometry) ---

Geom Title=USGS 10m DEM
Program Version=4.10

River Reach=RIGHTRMCRK      ,Main
Reach XY= 30
     1713159.345      289276.944     1713069.005      289448.358
     1712970.558      289915.114     1713033.101      290165.286
     1712939.286      290550.967     1712751.657       290671.42
     1712464.423      291191.454     1712274.478      291339.704
     1711438.255      291632.729     1710663.417       292083.27
     1710427.144      292082.112       1710145.7      292342.708
     1709993.976      292387.877     1709889.738      292694.801
     1709748.437      292781.666     1709647.673      292957.713
     1709257.359      293064.268     1708814.925      293261.162
     1708763.964      293398.989     1708558.962       293417.52
     1708042.403      293763.823     1707727.372      294102.018
     1707366.013      294293.122     1707166.802      294584.989
       1706884.2      294858.325     1706778.804      295128.186
     1706287.726      295445.534     1705716.731      296076.754
      1705421.39      296524.979     1704958.703      296897.069

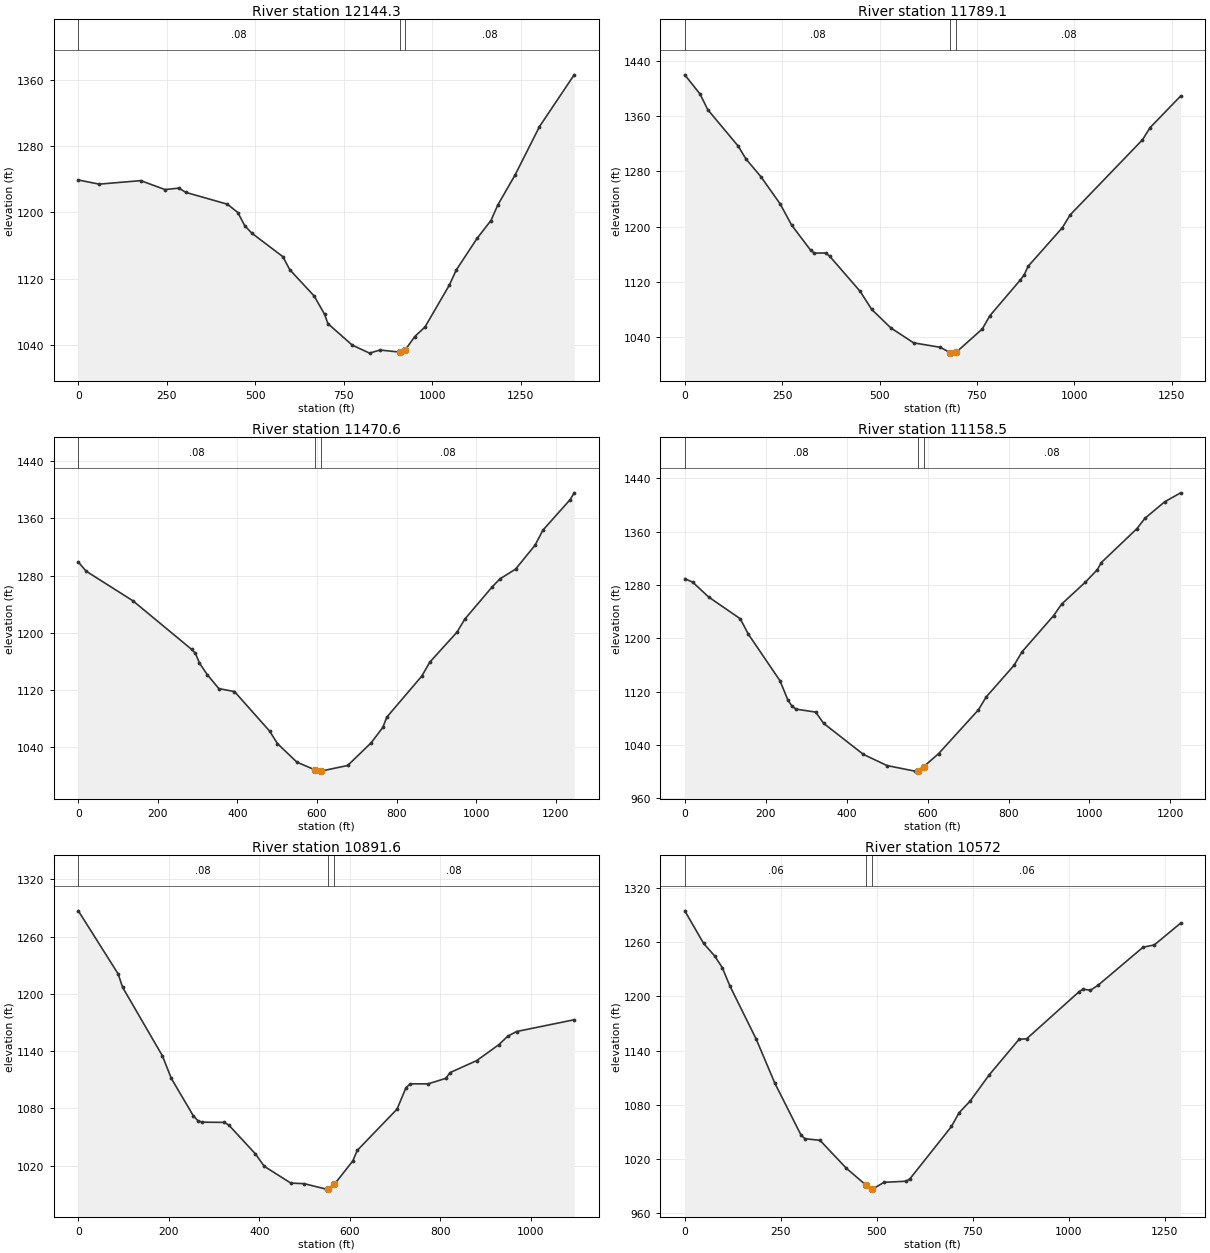
Type RM Length L Ch R = 1 ,12144.3 ,360.5,355.2,349.9
XS GIS Cut Line= 2
     1712374.806      288804.036     1713566.273      289540.084
#Sta/Elev= 30
       0 1239.19    58.8 1234.18   176.3 1238.41   244.8 1227.61     284 1229.37
   303.6 1224.22   421.1 1209.92   450.5  1199.9   470.1 1183.94   489.7 1175.04
   577.8  1146.5   597.4 1130.71     666 1099.05   695.4 1077.04   705.1 1065.58
   773.7 1039.63   822.7 1029.96     852 1033.74   908.5 1031.14   923.5 1033.91
     950 1049.87   979.4 1061.69  1047.9 1112.16  1067.5  1130.4  1126.3 1168.68
  1165.4 1190.19    1185 1209.13    1234 1245.58  1302.6 1303.76  1400.5 1366.27
#Mann= 3 , 0 , 0
       0     .08       0   908.5    .045       0   923.5     .08       0
Bank Sta=908.5,923.5
XS Rating Curve= 0 ,0
Exp/Cntr=0.3,0.1

Type RM Length L Ch R = 1 ,11789.1 ,326.8,318.5,310.1
XS GIS Cut Line= 2
     1712374.676      289399.289     1713584.235      289796.015
#Sta/Elev= 30
       0 1419.33    39.2 1391.53    58.8 1369.14   137.1 1316.35   156.7 1298.03
   195.8 1271.85   244.8 1232.85   274.2 1202.31   323.1 1165.83   332.9 1161.74
   362.3 1161.93   372.1 1157.17   450.4 1106.38   479.8 1080.43   528.8 1053.73
   587.5 1032.07   656.1  1025.6   681.9 1017.67   685.4  1017.2   696.9 1018.53
   763.8 1052.13   783.4 1071.37   861.7 1123.07   871.5 1130.38   881.3 1142.55
   969.4  1198.5     989 1216.73    1175 1325.45  1194.6 1343.06    1273 1388.71
#Mann= 3 , 0 , 0
       0     .08       0   681.9    .045       0   696.9     .08       0
Bank Sta=681.9,696.9
XS Rating Curve= 0 ,0
Exp/Cntr=0.3,0.1

Type RM Length L Ch R = 1 ,11470.6 ,307.6,312.1,316.6
XS GIS Cut Line= 2
     1712367.142      289955.292     1713612.123      289894.658
#Sta/Elev= 30
       0  1299.1    19.6 1286.32   137.4 1244.84   284.6 1177.08   294.4 1171.55
   304.2 1158.16   323.9 1141.85   353.3  1122.1   392.6 1118.03   480.9 1062.72
   500.6 1045.28   549.6 1019.25   594.9 1008.61   608.5 1006.78   609.9 1006.81
   677.2  1014.7   736.1 1046.36   765.5 1067.91   775.4  1082.2   863.7 1139.81
   883.3 1158.99     952 1201.11   971.6 1219.29  1040.4 1264.36    1060 1275.55
  1099.2 1289.19  1148.3 1322.74  1167.9 1343.64  1236.6 1386.45  1246.5 1395.84
#Mann= 3 , 0 , 0
       0     .08       0   594.9    .045       0   609.9     .08       0
Bank Sta=594.9,609.9
XS Rating Curve= 0 ,0
Exp/Cntr=0.3,0.1

Type RM Length L Ch R = 1 ,11158.5 ,263.3,266.9,270.6
XS GIS Cut Line= 2
     1712450.343      290134.185     1713661.337       290320.15
#Sta/Elev= 30
       0 1289.38    19.6 1284.14    58.8 1261.98   137.2 1229.28   156.8 1206.45
   235.2 1136.46   254.8 1107.52   264.6 1098.62   274.4 1093.95   323.4 1089.45
     343 1072.64   441.1 1026.18   499.9 1009.29   568.5 1000.98   575.4  1001.9
   590.4 1007.73   627.3 1027.29   725.3 1092.67   744.9 1112.25   813.5 1159.53
   833.1 1179.67   911.5 1234.12   931.1 1251.31     990 1284.26  1019.4 1302.93
  1029.2  1313.5  1117.4 1364.53    1137 1379.89    1186 1404.69  1225.2 1418.05
#Mann= 3 , 0 , 0
       0     .08       0   575.4    .045       0   590.4     .08       0
Bank Sta=575.4,590.4
XS Rating Curve= 0 ,0
Exp/Cntr=0.3,0.1

Type RM Length L Ch R = 1 ,10891.6 ,313.6,319.5,325.5
XS GIS Cut Line= 2
     1712428.539      290308.356     1713470.733      290646.828
#Sta/Elev= 30
       0 1287.01      88 1220.93    97.8 1206.95   185.9 1134.97   205.5 1111.42
   254.4 1072.11   264.2 1067.15   273.9  1065.6   322.9 1065.34   332.6 1062.55
   391.4 1032.33   410.9 1019.34   469.6 1001.77     499 1001.16   547.9  995.43
   550.9  995.89   565.9 1000.44   606.6 1025.01   616.4    1036   704.4 1079.28
     724 1101.62   733.8 1105.76   772.9 1105.71     812 1111.47   821.8 1117.59
   880.5 1130.12   929.5 1146.85     949 1155.63   968.6 1160.57  1095.8 1172.89
#Mann= 3 , 0 , 0
       0     .08       0   550.9    .045       0   565.9     .08       0
Bank Sta=550.9,565.9
XS Rating Curve= 0 ,0
Exp/Cntr=0.3,0.1

Type RM Length L Ch R = 1 ,10572   ,306.2,309.5,312.7
XS GIS Cut Line= 2
      1712348.88      290410.545     1713432.041      291112.551
#Sta/Elev= 30
       0 1294.79    48.9 1258.75    78.2 1244.65    97.8 1231.66   117.3 1211.68
   185.8 1152.78   234.7 1103.66   303.1 1046.01   312.9 1042.42     352 1040.63
   420.5 1009.71   472.4   990.8   487.4  986.72   488.9  986.57   518.3  994.08
   576.9  995.36   586.7  998.34   694.3 1055.99   713.8 1071.04   743.2 1084.28
     792 1112.86   870.3 1152.55   889.8 1153.05  1026.7  1205.3  1036.5 1208.02
  1056.1 1206.94  1075.6 1212.26    1193 1254.51  1222.3 1257.02  1290.8 1281.16
#Mann= 3 , 0 , 0
       0     .06       0   472.4    .045       0   487.4     .06       0
Bank Sta=472.4,487.4
XS Rating Curve= 0 ,0
Exp/Cntr=0.3,0.1

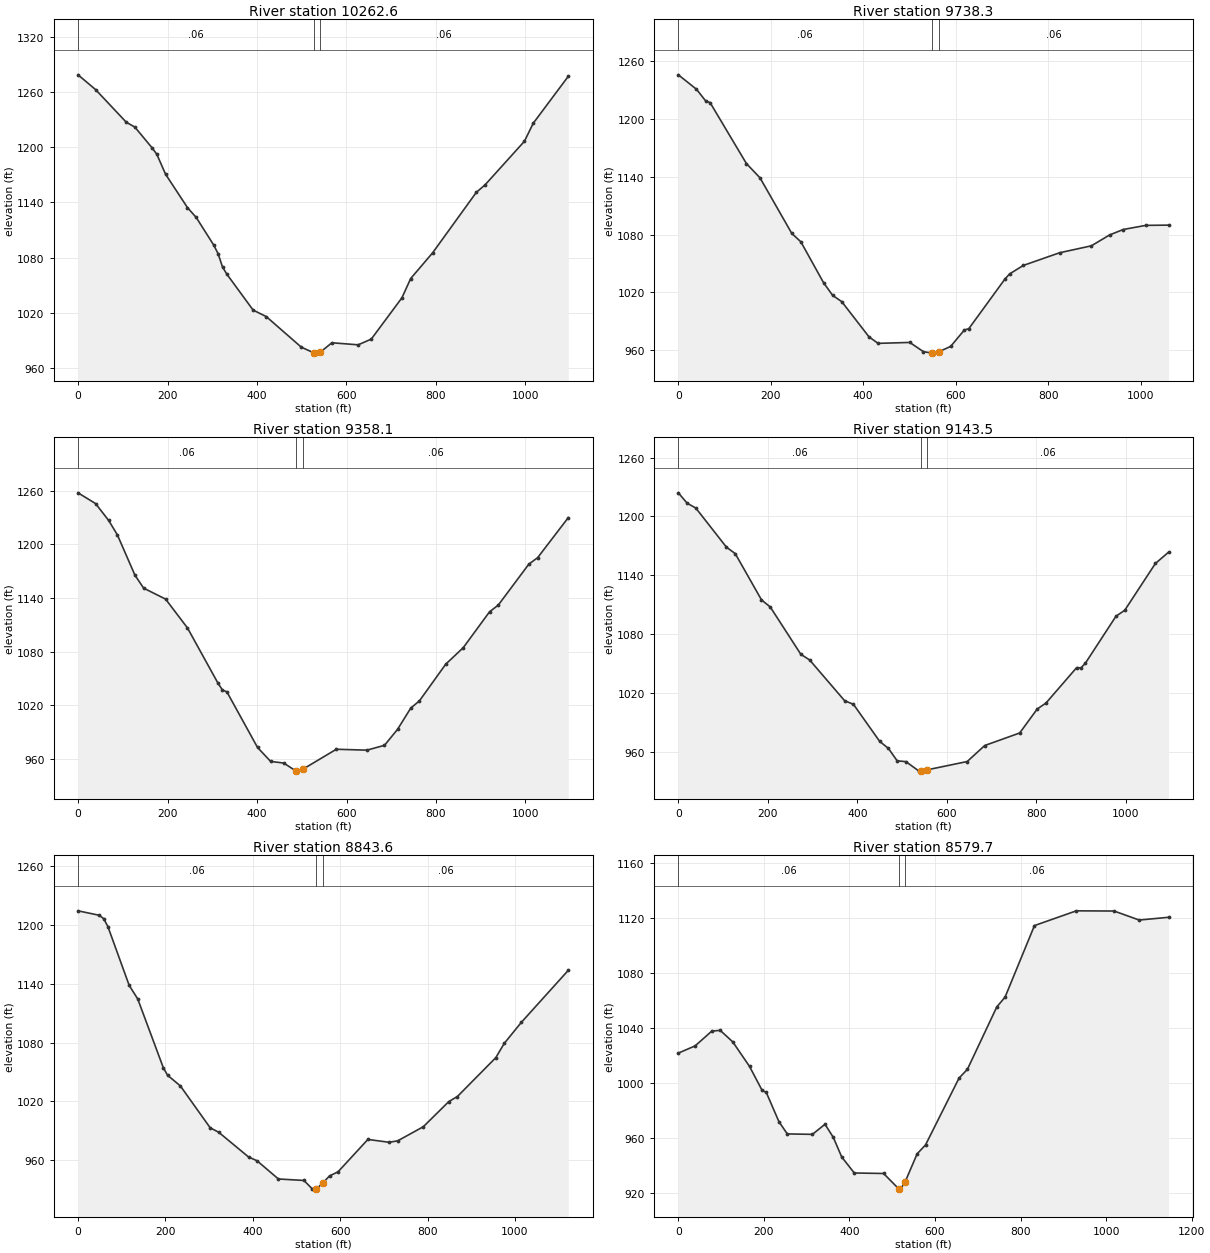
Type RM Length L Ch R = 1 ,10262.6 ,516.2,524.2,532.3
XS GIS Cut Line= 2
     1712228.907      290604.619     1713055.011       291324.54
#Sta/Elev= 30
       0 1279.13    39.1 1263.08   107.6 1227.56   127.2 1222.04   166.3 1199.06
   176.1 1192.47   195.7 1170.73   244.6 1134.38   264.2 1123.62   303.3 1093.55
   313.1 1084.11   322.9 1069.71   332.6 1061.85   391.4 1022.64   420.7 1015.61
     499  982.29   526.6  976.16   528.3  975.76   541.6  976.87   567.5  987.05
   626.2  984.82   655.5  991.06     724 1036.09   743.6  1057.1   792.5 1085.04
   890.3 1151.01   909.9 1159.22   997.9 1206.74  1017.5 1226.33  1095.8 1277.46
#Mann= 3 , 0 , 0
       0     .06       0   526.6    .045       0   541.6     .06       0
Bank Sta=526.6,541.6
XS Rating Curve= 0 ,0
Exp/Cntr=0.3,0.1

Type RM Length L Ch R = 1 ,9738.3  ,376.5,380.2,383.8
XS GIS Cut Line= 2
     1712023.401       290842.35     1712521.405      291778.707
#Sta/Elev= 30
       0 1246.14    39.3 1231.13    58.9 1219.16    68.7 1217.28   147.3 1153.91
   176.8    1139   245.5 1081.27   265.1 1072.56   314.2 1030.05   333.9 1016.86
   353.5 1010.41   412.4  973.85   432.1  967.01   500.8  967.96   530.3  958.35
     549  956.93   549.9  956.85     564  958.35   589.2  963.83   618.7  980.83
   628.5  982.29     707  1034.1   716.9 1039.24   746.3 1047.99   824.9 1061.18
   893.6  1068.4   932.9 1079.64   962.4 1085.35  1011.4 1089.65  1060.6 1089.91
#Mann= 3 , 0 , 0
       0     .06       0     549    .045       0     564     .06       0
Bank Sta=549,564
XS Rating Curve= 0 ,0
Exp/Cntr=0.3,0.1

Type RM Length L Ch R = 1 ,9358.1  ,215.7,214.6,213.5
XS GIS Cut Line= 2
      1711764.15      290974.443     1712117.255      292011.633
#Sta/Elev= 30
       0 1257.66    39.1 1245.66    68.5 1226.74      88 1210.53   127.2 1165.51
   146.7 1151.03   195.6 1138.82   244.6 1106.52     313 1044.55   322.8 1037.06
   332.6  1035.1   401.1  972.89   430.4  957.29   459.8  955.42   486.9   946.6
   489.1  946.41   501.9  948.38   577.2  970.87   645.6  969.88   684.8  975.24
   714.1  993.15   743.5 1016.84     763 1025.02   821.7 1065.99   860.9 1084.48
   919.6 1124.55   939.1 1132.05  1007.6 1177.95  1027.2 1185.16  1095.6 1229.89
#Mann= 3 , 0 , 0
       0     .06       0   486.9    .045       0   501.9     .06       0
Bank Sta=486.9,501.9
XS Rating Curve= 0 ,0
Exp/Cntr=0.3,0.1

Type RM Length L Ch R = 1 ,9143.5  ,301.5,299.9,297.9
XS GIS Cut Line= 2
     1711522.126      291000.513     1711920.392      292021.354
#Sta/Elev= 30
       0 1224.05    19.6 1213.54    39.1 1208.53   107.6 1168.69   127.2 1162.17
   185.9 1115.06   205.5 1107.81   273.9 1059.62   293.5  1053.9   371.8 1012.34
   391.4 1008.76     450  971.05   469.6  963.86   489.2   951.2   508.8  950.36
   538.1   940.7   541.5  940.78   556.5  942.04   645.7  950.47   684.9  966.77
   763.1  979.54   802.3 1003.97   821.8    1010   890.3 1046.04   900.1 1045.85
   909.9  1050.6   978.4 1098.46   997.9 1104.46  1066.4 1152.12  1095.8 1163.59
#Mann= 3 , 0 , 0
       0     .06       0   541.5    .045       0   556.5     .06       0
Bank Sta=541.5,556.5
XS Rating Curve= 0 ,0
Exp/Cntr=0.3,0.1

Type RM Length L Ch R = 1 ,8843.6  ,264.1,264,264.1
XS GIS Cut Line= 2
     1711219.538      291130.978     1711709.211      292140.652
#Sta/Elev= 30
       0 1214.45    48.8 1209.88    58.6 1206.48    68.3 1198.38   117.1 1138.28
   136.6 1124.51   195.2 1054.26   204.9  1046.6   234.2 1035.69   302.5  992.93
     322  988.37   390.3  963.14   409.8  959.24   458.6  940.68   517.2  939.15
   536.7  930.31   545.8  930.48   560.8  936.83   575.7  943.79   595.2     948
   663.5  981.04   712.3  978.13   731.8  979.63   790.4  994.03   848.9 1019.77
   868.4 1024.86   956.3 1064.53   975.8 1079.19  1014.8 1100.58  1122.2 1153.68
#Mann= 3 , 0 , 0
       0     .06       0   545.8    .045       0   560.8     .06       0
Bank Sta=545.8,560.8
XS Rating Curve= 0 ,0
Exp/Cntr=0.3,0.1

Type RM Length L Ch R = 1 ,8579.7  ,368.2,366.6,365.1
XS GIS Cut Line= 2
     1711000.822      291288.584     1711510.098      292314.956
#Sta/Elev= 30
       0 1021.83    39.2 1027.07    78.3 1037.86    97.9 1038.37   127.3 1029.97
   166.5 1012.09   195.9  994.65   205.6  993.18     235     972   254.6  962.99
   313.4  962.67   342.8  970.01   362.3  960.44   381.9  946.18   411.3  934.54
   479.8  934.18   514.7  923.15     519  922.79   529.7  927.77   558.2   948.5
   577.8  954.98   656.1 1003.62   675.7 1010.05   744.3  1055.4   763.8 1062.65
   832.4 1114.67   930.3 1125.41  1018.5 1125.26  1077.2  1118.7  1145.8  1120.7
#Mann= 3 , 0 , 0
       0     .06       0   514.7    .045       0   529.7     .06       0
Bank Sta=514.7,529.7
XS Rating Curve= 0 ,0
Exp/Cntr=0.3,0.1

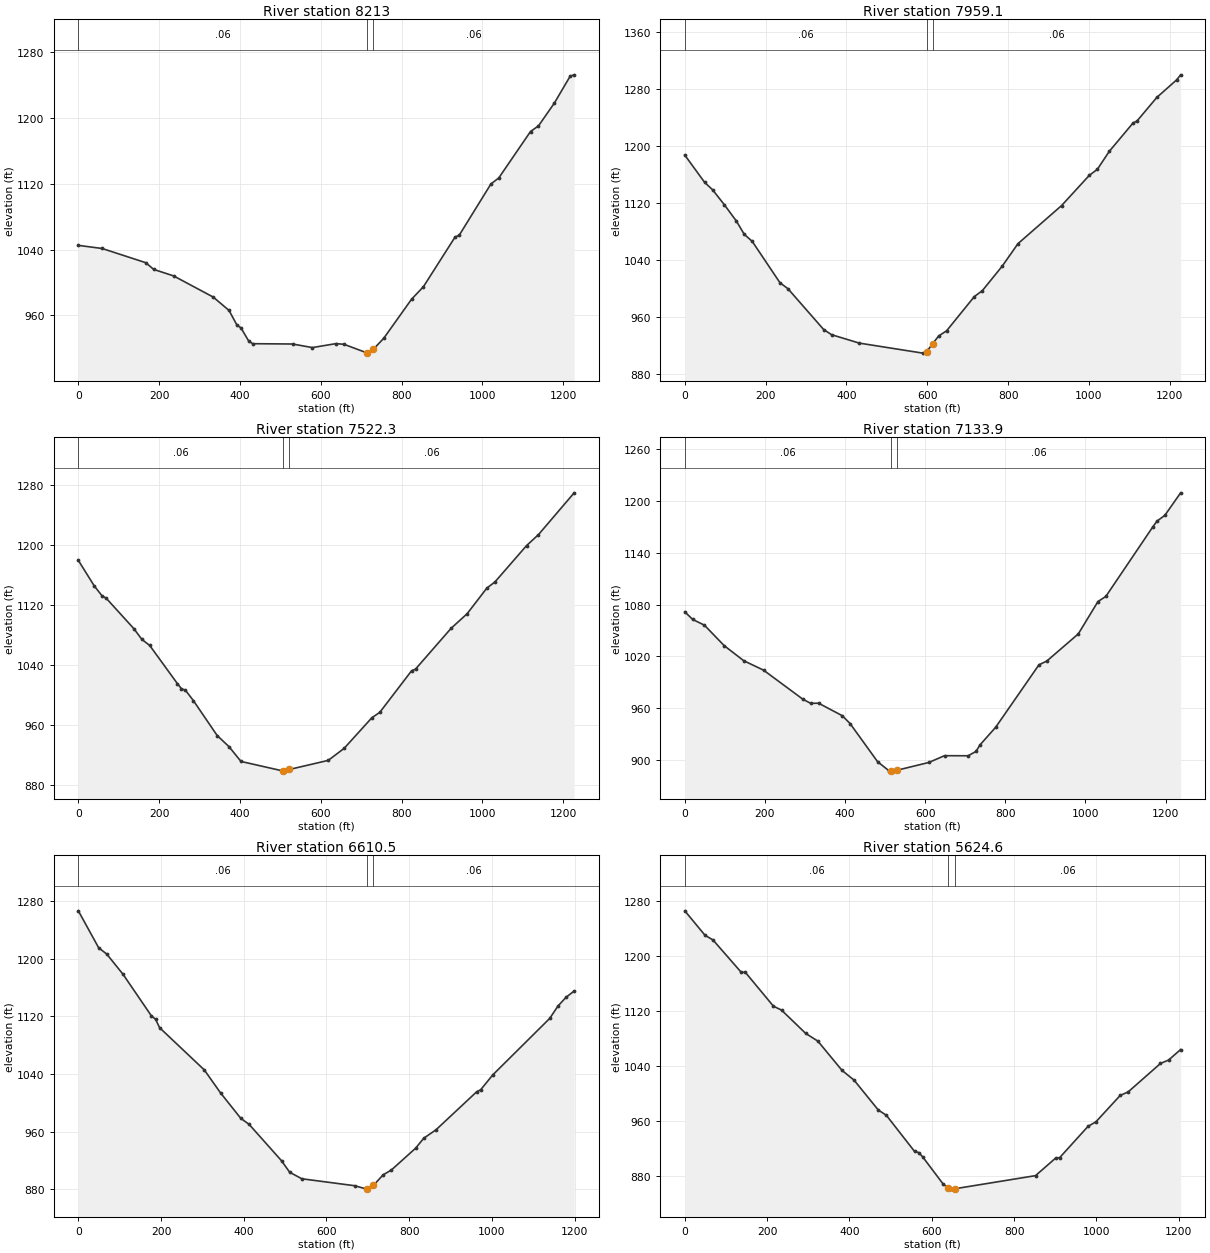
Type RM Length L Ch R = 1 ,8213    ,254,253.9,253.8
XS GIS Cut Line= 2
     1710549.179      291292.233     1711168.584      292351.421
#Sta/Elev= 30
       0 1045.06    58.9 1041.26   166.9 1023.99   186.5 1015.84   235.6 1007.97
   333.8  982.22     373  965.94   392.6  948.07   402.5  944.76   422.1  928.35
   431.9  925.54   530.1  925.17   579.2  920.84     638  925.66   657.7  924.76
   715.4  914.17   716.6  914.08   730.4  918.95   755.8  932.14   824.6  979.58
     854  994.82   932.5 1055.33   942.3 1057.16  1020.9  1119.6  1040.5 1127.04
    1119 1183.44  1138.7 1190.26  1177.9 1217.91  1217.2 1250.74    1227 1252.33
#Mann= 3 , 0 , 0
       0     .06       0   715.4    .045       0   730.4     .06       0
Bank Sta=715.4,730.4
XS Rating Curve= 0 ,0
Exp/Cntr=0.3,0.1

Type RM Length L Ch R = 1 ,7959.1  ,437.3,436.8,436.3
XS GIS Cut Line= 2
     1710399.939      291532.582     1711019.344       292591.77
#Sta/Elev= 30
       0 1187.13    49.1 1148.85    68.7 1138.51    98.2 1117.26   127.6 1094.65
   147.2 1075.94   166.9 1066.09   235.6    1008   255.2  999.75   343.6  942.49
   363.2  935.22   431.9   923.4     589  909.36   598.4  911.32   613.4  922.65
   628.2  933.39   647.9   940.7   716.6  988.74   736.2  996.91   785.3 1031.23
   824.6 1062.96   932.5 1116.38  1001.2 1158.84  1020.9 1167.15  1050.3 1192.27
  1109.2 1232.14    1119 1234.91  1168.1 1268.01  1217.2 1292.69    1227 1299.71
#Mann= 3 , 0 , 0
       0     .06       0   598.4    .045       0   613.4     .06       0
Bank Sta=598.4,613.4
XS Rating Curve= 0 ,0
Exp/Cntr=0.3,0.1

Type RM Length L Ch R = 1 ,7522.3  ,397.4,388.4,379.5
XS GIS Cut Line= 2
     1710063.876      291738.456     1710683.281      292797.645
#Sta/Elev= 30
       0 1179.14    39.3 1145.26    58.9 1131.79    68.7 1128.94   137.4  1088.3
   157.1  1074.1   176.7 1065.89   245.4    1015   255.2 1008.39     265  1006.4
   284.7  992.62   343.6  946.12     373  931.25   402.5  911.66   507.3  898.87
   510.4  898.77   522.3  900.99   618.4  913.07   657.7  929.02   726.4  969.78
     746  976.96   824.6 1032.22   834.4 1034.48   922.7 1088.88     962 1108.05
    1011 1142.28  1030.7 1150.28  1109.2 1198.76  1138.7 1213.38    1227 1268.97
#Mann= 3 , 0 , 0
       0     .06       0   507.3    .045       0   522.3     .06       0
Bank Sta=507.3,522.3
XS Rating Curve= 0 ,0
Exp/Cntr=0.3,0.1

Type RM Length L Ch R = 1 ,7133.9  ,519,523.4,527.8
XS GIS Cut Line= 2
     1709589.869      292060.747     1710574.148      292811.096
#Sta/Elev= 30
       0 1071.69    19.6 1062.89    49.1 1056.16    98.2 1032.51   147.3 1014.91
   196.5 1004.06   294.7  970.32   314.3  965.54     334   965.7   392.9  951.24
   412.6  942.08   481.3  897.81   510.8   886.9   514.2  886.94   529.2  887.88
     609  896.93   648.3  904.81   707.2  904.72   726.9  909.74   736.7  917.22
     776  937.78     884 1010.19   903.7  1014.6   982.3 1046.11  1031.4 1083.62
    1051 1089.55  1168.9 1170.65  1178.7 1176.88  1198.4 1183.63  1237.7 1209.72
#Mann= 3 , 0 , 0
       0     .06       0   514.2    .045       0   529.2     .06       0
Bank Sta=514.2,529.2
XS Rating Curve= 0 ,0
Exp/Cntr=0.3,0.1

Type RM Length L Ch R = 1 ,6610.5  ,976.5,985.9,995.4
XS GIS Cut Line= 2
     1709282.065      292252.506     1710079.088      293147.955
#Sta/Elev= 30
       0  1266.8    49.1  1215.5    68.8 1206.64   108.1 1178.59   176.9 1120.61
   186.7 1116.14   196.5 1104.39   304.6 1045.66   343.9 1013.71     393  978.26
   412.7  970.17   491.3  919.45     511  903.46   540.4  894.41   668.2  884.75
   697.6  880.02   698.4  880.16   713.4   885.2     737  899.93   756.6  906.45
   815.6  936.98   835.2  950.79   864.7  962.44     963 1015.26   972.8 1018.17
  1002.3 1038.94  1139.8 1117.35  1159.5 1134.34  1179.1  1146.6  1198.8 1155.33
#Mann= 3 , 0 , 0
       0     .06       0   698.4    .045       0   713.4     .06       0
Bank Sta=698.4,713.4
XS Rating Curve= 0 ,0
Exp/Cntr=0.3,0.1

Type RM Length L Ch R = 1 ,5624.6  ,264.7,268.3,268.8
XS GIS Cut Line= 2
     1708737.423      292605.559     1709103.407      293753.144
#Sta/Elev= 30
       0 1265.21      49 1229.82    68.6  1222.9   137.1 1176.08   146.9 1176.18
   215.4 1126.88     235 1121.27   293.8 1087.42   323.2 1076.34   381.9 1033.88
   411.3 1019.66   470.1  976.36   489.6   968.8   558.2  916.32     568  914.78
   577.8  908.52   626.8   869.7   640.3  862.71   646.3  861.69   655.3  862.16
     852  881.25     901  906.77   910.7  907.36   979.3  952.54   998.9  959.39
  1057.6  997.47  1077.2 1002.71  1155.6 1043.92  1175.2 1048.83  1204.5 1064.09
#Mann= 3 , 0 , 0
       0     .06       0   640.3    .045       0   655.3     .06       0
Bank Sta=640.3,655.3
XS Rating Curve= 0 ,0
Exp/Cntr=0.3,0.1

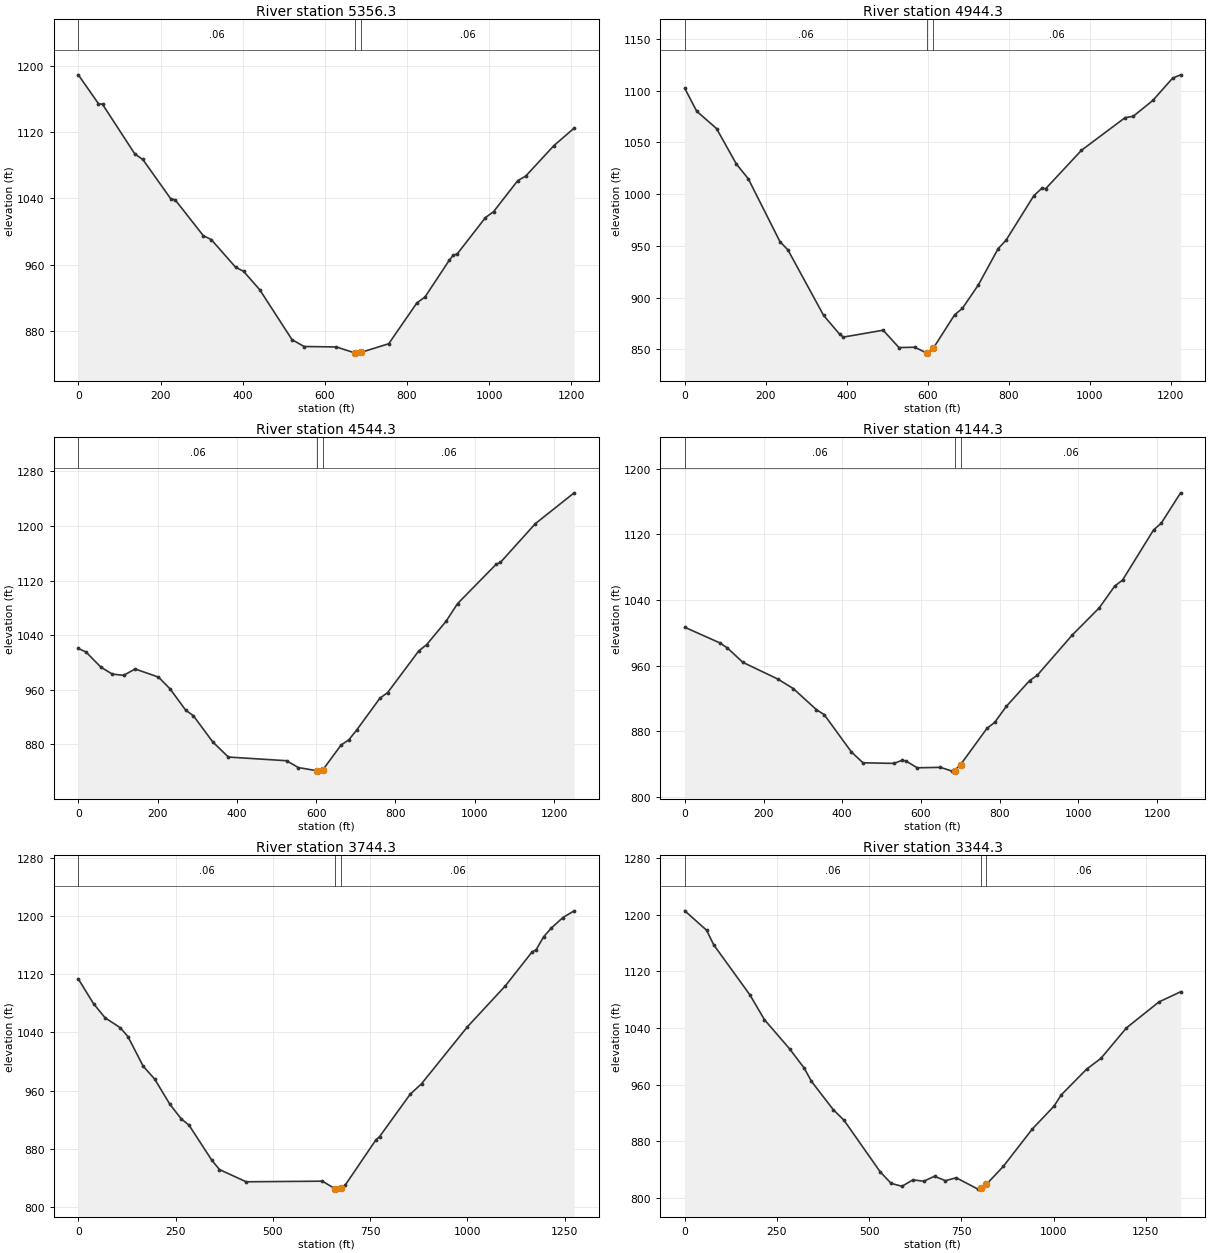
Type RM Length L Ch R = 1 ,5356.3  ,423.7,412,403.5
XS GIS Cut Line= 2
     1708548.424      292749.402     1708936.696      293891.982
#Sta/Elev= 30
       0  1188.8      49 1154.07    58.9 1153.28   137.4 1093.59     157 1086.84
   225.6 1039.08   235.5 1038.39   304.1  995.16   323.8  990.29   382.6  957.18
   402.2   952.2   441.5  930.02     520  869.96   549.4  861.62   627.9  861.12
   673.7   853.8     677  853.66   688.7  854.68   755.4  864.95   824.1  914.19
   843.7  921.22   902.6  965.35   912.4  971.44   922.2  973.13   990.9  1016.9
  1010.5 1023.94  1069.4 1061.35    1089  1066.9  1157.7 1103.67  1206.8 1124.62
#Mann= 3 , 0 , 0
       0     .06       0   673.7    .045       0   688.7     .06       0
Bank Sta=673.7,688.7
XS Rating Curve= 0 ,0
Exp/Cntr=0.3,0.1

Type RM Length L Ch R = 1 ,4944.3  ,397.7,400,402.3
XS GIS Cut Line= 2
     1708028.661      293056.941     1708783.679      294020.585
#Sta/Elev= 30
       0 1102.08    29.4 1080.05    78.4 1063.27   127.3 1029.02   156.7 1014.78
     235  953.95   254.6  946.02   342.8  882.68     382  864.65   391.7  861.76
   489.7  868.41   528.8  851.61     568  851.95   597.4  846.25   598.6  846.42
   613.6  851.01     666  883.19   685.6  889.64   724.7  912.12   773.7  947.24
   793.3  955.43   861.8  998.42   881.4 1005.51   891.2 1005.24   979.4 1042.27
  1087.1 1073.84  1106.7 1074.99  1155.6 1090.43  1204.6 1112.04  1224.2 1115.19
#Mann= 3 , 0 , 0
       0     .06       0   598.6    .045       0   613.6     .06       0
Bank Sta=598.6,613.6
XS Rating Curve= 0 ,0
Exp/Cntr=0.3,0.1

Type RM Length L Ch R = 1 ,4544.3  ,402.6,400,397.4
XS GIS Cut Line= 3
     1707792.063      293212.817     1707817.613      293343.837
     1708411.449      294290.262
#Sta/Elev= 30
       0 1020.51    19.1 1015.54    57.2  993.07    85.8     983   114.4  981.23
   143.3  990.53   202.1  978.63   231.5  961.31   270.7  930.26   290.3  921.96
   339.3  883.52   378.5  861.48   525.5   856.1   554.9   846.1   601.2   841.5
   603.9  840.86   616.2  842.26   662.7  879.05   682.3  886.72   701.9  900.86
   760.7  947.64   780.4  956.01   858.8 1016.97   878.4    1026   927.4 1060.19
   956.8 1086.36  1054.8 1144.33  1064.6 1146.51  1152.8 1203.36  1250.8 1248.56
#Mann= 3 , 0 , 0
       0     .06       0   601.2    .045       0   616.2     .06       0
Bank Sta=601.2,616.2
XS Rating Curve= 0 ,0
Exp/Cntr=0.3,0.1

Type RM Length L Ch R = 1 ,4144.3  ,397.7,400,402.3
XS GIS Cut Line= 2
     1707367.234      293492.704      1708151.58      294478.534
#Sta/Elev= 30
       0 1006.83    88.6  987.93   108.3  981.62   147.6  964.11   236.2  943.81
   275.6   932.2   334.6  906.46   354.3  900.42   423.2  855.06   452.7  841.78
   531.5  841.05   551.2  844.68     561  844.24   590.5  835.71   649.6  836.22
   679.1  831.63   685.6  832.38   700.6  839.51   767.7  883.71   787.4  891.02
   816.9  910.46   875.9   941.8   895.6  948.42   984.2  997.29  1053.1 1030.53
  1092.5 1057.11  1112.2 1064.29  1190.9 1125.31  1210.6 1133.67  1259.8  1170.6
#Mann= 3 , 0 , 0
       0     .06       0   685.6    .045       0   700.6     .06       0
Bank Sta=685.6,700.6
XS Rating Curve= 0 ,0
Exp/Cntr=0.3,0.1

Type RM Length L Ch R = 1 ,3744.3  ,406.9,400,393.1
XS GIS Cut Line= 2
     1707098.944       293669.46     1707791.671      294739.285
#Sta/Elev= 30
       0 1113.36    39.2 1079.34    68.6 1060.12   107.8 1046.31   127.4 1034.27
   166.7  993.45   196.1   975.9   235.3  941.13   264.7   920.9   284.3  912.58
   343.1  864.16   362.8  851.34   431.4  834.53   627.4  835.36   660.2  824.76
   666.7  824.43   675.2  825.36   686.3  830.21   764.7     892   774.5  896.76
     853  954.89   882.4  969.46    1000 1047.56    1098 1104.15  1166.7 1150.84
  1176.5 1153.37  1196.1 1171.48  1215.7 1183.33  1245.1 1197.67  1274.5 1207.08
#Mann= 3 , 0 , 0
       0     .06       0   660.2    .045       0   675.2     .06       0
Bank Sta=660.2,675.2
XS Rating Curve= 0 ,0
Exp/Cntr=0.3,0.1

Type RM Length L Ch R = 1 ,3344.3  ,874.9,875.5,876
XS GIS Cut Line= 2
     1706578.334       294012.45     1707617.757      294865.283
#Sta/Elev= 30
       0 1205.81    58.9 1178.51    78.5 1157.66   176.6 1086.92   215.9 1051.88
   284.6 1010.35   323.9  983.22   343.5   964.6   402.4  924.69   431.8  909.54
     530  836.48   559.4  820.33   588.8  816.15   618.3  825.18   647.7   823.4
   677.2  830.31   706.6  824.09     736  828.22   794.9  812.14   802.6  813.38
   817.6  818.81   863.6  844.27   942.1  897.05    1001  929.41  1020.7  945.41
  1089.4  981.76  1128.6  997.23  1197.3 1040.08  1285.6  1076.9  1344.5 1091.32
#Mann= 3 , 0 , 0
       0     .06       0   802.6    .045       0   817.6     .06       0
#XS Ineff= 2 , 0
           678.3  829.61
Permanent Ineff=
       F       F
Bank Sta=802.6,817.6
XS Rating Curve= 0 ,0
Exp/Cntr=0.3,0.1

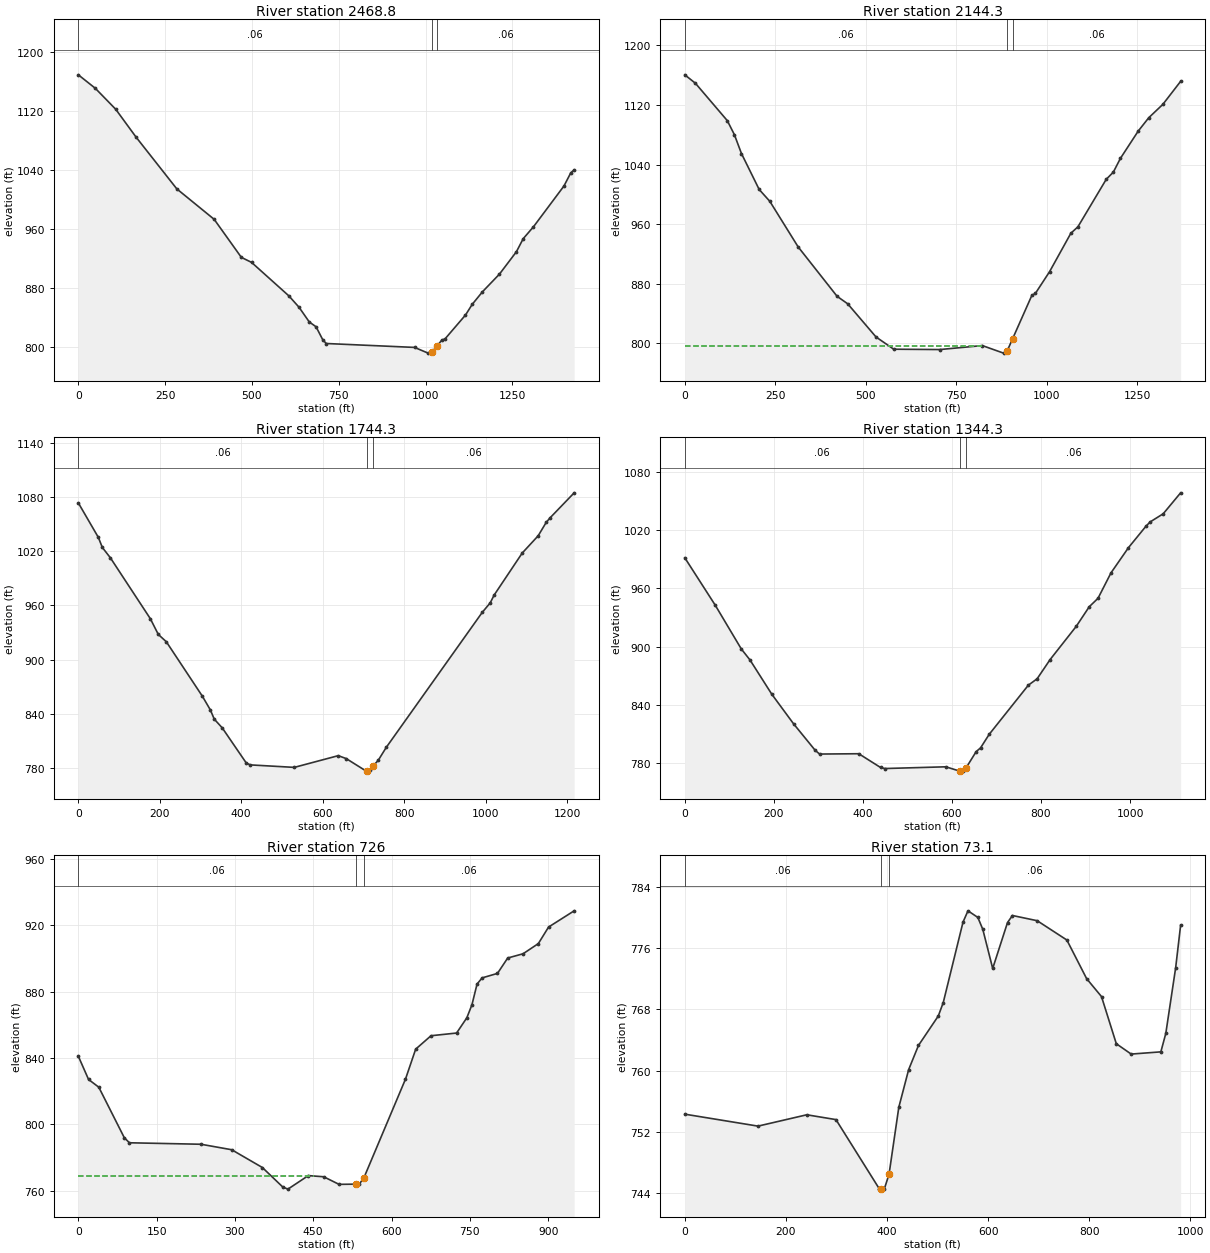
Type RM Length L Ch R = 1 ,2468.8  ,320.5,324.5,328.6
XS GIS Cut Line= 2
     1705936.376      294493.178     1706978.802      295468.901
#Sta/Elev= 30
       0 1168.96    48.9 1150.71   107.6 1122.38   166.2 1084.65   283.6 1014.54
   391.2  973.31   469.4  921.85   498.8  915.05   606.3  869.69   635.7  854.21
     665  834.41   684.6  827.83   704.1   810.1   713.9  805.22   968.2  799.92
  1007.3  792.19  1017.3  793.16  1032.3   801.6  1046.4  809.63  1056.2   811.6
  1114.9  843.76  1134.4  858.31  1163.8  875.26  1212.7  899.16  1261.6  929.51
  1281.1  947.15  1310.5  963.15  1398.5  1018.5    1418 1036.23  1427.8  1040.3
#Mann= 3 , 0 , 0
       0     .06       0  1017.3    .045       0  1032.3     .06       0
Bank Sta=1017.3,1032.3
XS Rating Curve= 0 ,0
Exp/Cntr=0.3,0.1

Type RM Length L Ch R = 1 ,2144.3  ,404.4,400,395.6
XS GIS Cut Line= 2
     1705859.227      294671.062     1706711.379      295744.532
#Sta/Elev= 30
       0 1160.51    29.4 1149.16   117.5 1098.96   137.1 1080.11   156.6 1054.81
   205.6  1006.5     235  990.62   313.3   929.4     421     863   450.3  852.93
   528.6  808.38   577.6  791.95   704.9  791.49   822.4  796.84   881.1  786.69
   890.9  789.36   890.9  789.37   905.9  805.72   959.4  864.27   969.2  866.96
  1008.4  896.14  1067.1  947.64  1086.7  956.38    1165  1020.2  1184.6  1029.8
  1204.2 1048.32  1253.1 1084.76  1282.5 1102.88  1321.6  1120.9  1370.6 1151.75
#Mann= 3 , 0 , 0
       0     .06       0   890.9    .045       0   905.9     .06       0
#XS Ineff= 2 , 0
           820.9  796.78
Permanent Ineff=
       F       F
Bank Sta=890.9,905.9
XS Rating Curve= 0 ,0
Exp/Cntr=0.3,0.1

Type RM Length L Ch R = 1 ,1744.3  ,400,400,400
XS GIS Cut Line= 2
     1705574.878       295167.16     1706500.758       295957.69
#Sta/Elev= 30
       0 1073.32    49.1 1035.25    58.9  1024.1    78.6 1012.71   176.7  945.43
   196.4  927.93     216   919.9   304.4  859.79     324  844.66   333.8  834.34
   353.4  824.66   412.4  785.84   422.2  783.78   530.2  781.03   638.2  793.98
   657.8  790.74   706.9  776.89   709.5  777.15   716.7   777.9   724.5  782.94
   736.4  788.87     756  803.09   991.6  952.26  1011.3  962.86  1021.1  971.59
  1089.8 1017.86  1129.1 1037.02  1148.7 1051.77  1158.5 1056.94  1217.4 1084.47
#Mann= 3 , 0 , 0
       0     .06       0   709.5    .045       0   724.5     .06       0
#XS Ineff= 2 , 0
          638.62  793.75
Permanent Ineff=
       F       F
Bank Sta=709.5,724.5
XS Rating Curve= 0 ,0
Exp/Cntr=0.3,0.1

Type RM Length L Ch R = 1 ,1344.3  ,620.6,618.2,615.9
XS GIS Cut Line= 2
     1705373.636      295518.262      1706220.15      296241.678
#Sta/Elev= 30
       0  991.56    68.4  942.72     127  897.63   146.5  886.33   195.4  851.08
   244.2  820.71     293  793.26   302.8  789.52   390.7  789.85   439.6  775.69
   449.3  774.61   586.1  776.39   617.1     772   625.1  771.94   632.1  775.63
   654.4  792.06   664.2  795.87   683.7  809.88   771.6  860.45   791.2  866.98
   820.5  886.84   879.1  920.98   908.4  941.23   927.9   949.8   957.2  976.09
   996.3 1001.94  1035.4  1023.9  1045.1 1028.49  1074.4 1036.86  1113.5 1058.42
#Mann= 3 , 0 , 0
       0     .06       0   617.1    .045       0   632.1     .06       0
Bank Sta=617.1,632.1
XS Rating Curve= 0 ,0
Exp/Cntr=0.3,0.1

Type RM Length L Ch R = 1 ,726     ,654,653,652
XS GIS Cut Line= 2
     1705033.151       296108.93     1705815.647      296647.265
#Sta/Elev= 30
       0  841.02    19.6  827.01    39.2  822.34    88.1  791.83    97.9   788.8
     235  787.91   293.8   784.6   352.5  773.88   391.7  762.08   401.5  760.83
   440.6     769     470  768.29   499.4  763.71     532  763.84   538.5  764.02
     547  767.63   626.7  827.22   646.2   845.3   675.6   853.4   724.6  855.03
   744.2  864.22     754  872.09   763.8   884.6   773.5  888.31   802.9  891.02
   822.5   900.3   851.9  902.86   881.2  909.01   900.8  918.99   949.8  928.78
#Mann= 3 , 0 , 0
       0     .06       0     532    .045       0     547     .06       0
#XS Ineff= 2 , 0
          451.73  768.76
Permanent Ineff=
       F       F
Bank Sta=532,547
XS Rating Curve= 0 ,0
Exp/Cntr=0.3,0.1

Type RM Length L Ch R = 1 ,73.1    ,61.5,73.1,84.7
XS GIS Cut Line= 4
      1704786.77      296548.412      1704917.45      296795.966
     1705049.304      296873.527     1705587.017      296768.888
#Sta/Elev= 30
       0  754.32   144.8  752.76   241.3  754.24     299  753.61   385.1  744.54
     389  744.55   394.7  744.57     404  746.49   423.3  755.22   442.7  760.12
   462.2  763.29   501.4  767.13   511.2  768.88   550.3  779.38   560.1  780.85
   579.6  779.99   589.4  778.44     609  773.33   638.3  779.32   648.1  780.24
     697  779.56   755.7  777.04   794.8     772   824.2  769.66   853.5  763.51
   882.9  762.16   941.6  762.45   951.4  764.86   970.9  773.43   980.7  778.97
#Mann= 3 , 0 , 0
       0     .06       0     389    .045       0     404     .06       0
Bank Sta=389,404
XS Rating Curve= 0 ,0
Exp/Cntr=0.3,0.1

Chan Stop Cuts=-1
Use User Specified Reach Order=0
Composite Channel Slope=5